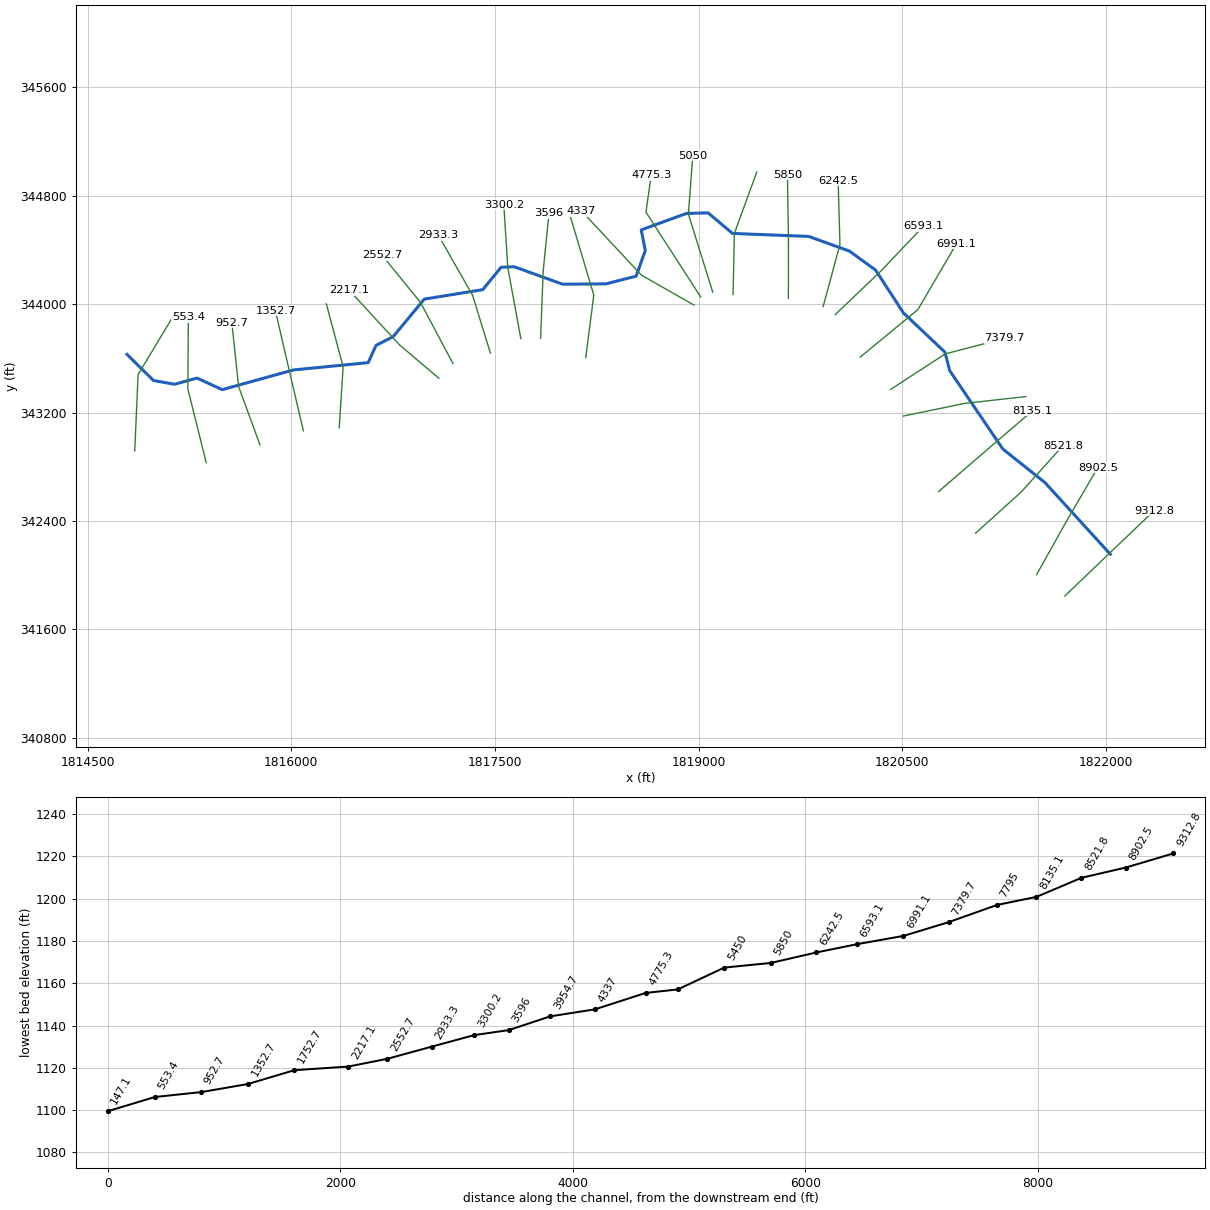
--- NP11.prj (project) ---

Proj Title=NP11
Current Plan=p01
Default Exp/Contr=0,0
English Units
Geom File=g01
Flow File=f01
Plan File=p01
BEGIN DESCRIPTION:
END DESCRIPTION:
DSS Export Rating Curves= 0
DSS Export Rating Curve Sorted= 0
DSS Export Volume Flow Curves= 0
DXF OffsetX= 0
DXF OffsetY= 0
DXF ScaleX= 0
DXF ScaleY= 0

--- NP11.p01 (plan) ---

Plan Title=Floodplain
Program Version=4.00
Geom File=g01
Flow File=f01
K Sum by GR=0
Std Step Tol=0.01
Critical Tol=0.01
Num of Std Step Trials=20
Max Error Tol=0.3
Flow Tol Ratio=0.001
Split Flow NTrial=30
Split Flow Tol=0.02
Split Flow Ratio=0.02
Log Output Level=0
Friction Slope Method=1
Unsteady Friction Slope Method=2
Unsteady Bridges Friction Slope Method=1
Global Log Level=0
CheckData=False
Run HTab=0
Run UNet=0
Run PostProcess=0
UNET Theta=0
UNET Theta Warmup=0
UNET ZTol=0
UNET ZSATol=0
UNET MxIter=0
UNET MaxInSteps=0
UNET DtIC=0
UNET DtMin=0
UNET MaxCRTS=0
UNET WFStab=0
UNET SFStab=0
UNET WFX=0
UNET SFX=0
UNET DSS MLevel=0
UNET DZMax Abort=0
UNET Convert EG Bridges=0
UNET Use Existing IB Tables=0
UNET Froude Limit=0
UNET Froude Power=0
Write IC File=0
Echo Input=False
Echo Output=False
Write Detailed=0

--- NP11.f01 (steady flow) ---

Flow Title=NFF Regression Equation
Program Version=4.00
Number of Profiles=1
Profile Names=P100yr
River Rch & RM=NP11,Main      ,9312.8
     722
River Rch & RM=NP11,Main      ,7379.7
792.5736
River Rch & RM=NP11,Main      ,6991.1
1131.344
River Rch & RM=NP11,Main      ,5450
1165.694
River Rch & RM=NP11,Main      ,147.1
1290.972
Boundary for River Rch & Prof#=NP11,Main      ,1
Up Type=0
Dn Type=3
Dn Slope=0.010827

--- NP11.g01 (geometry) ---

Geom Title=USGS 3m DEM
Program Version=4.00

River Reach=NP11            ,Main
Reach XY= 30
     1822031.862      342154.382     1821549.802      342683.684
      1821239.46      342931.436      1820848.98      343508.812
     1820813.075       343646.45     1820507.879      343935.687
      1820303.22      344251.039     1820110.234      344391.866
      1819809.72      344500.199     1819249.197      344522.142
      1819069.67      344673.742     1818910.091      344669.753
     1818576.782      344548.341      1818606.89      344396.473
     1818539.376      344206.826     1818316.516      344150.019
     1817997.225      344147.589     1817642.961      344275.857
     1817545.233      344272.803     1817410.045      344107.235
      1816979.18      344037.419     1816749.785       343760.15
     1816624.116      343696.318     1816566.268      343568.655
      1816015.72      343514.797     1815491.103       343369.18
     1815305.591      343454.954     1815140.028      343409.075
     1814984.438      343437.002     1814790.257      343629.938

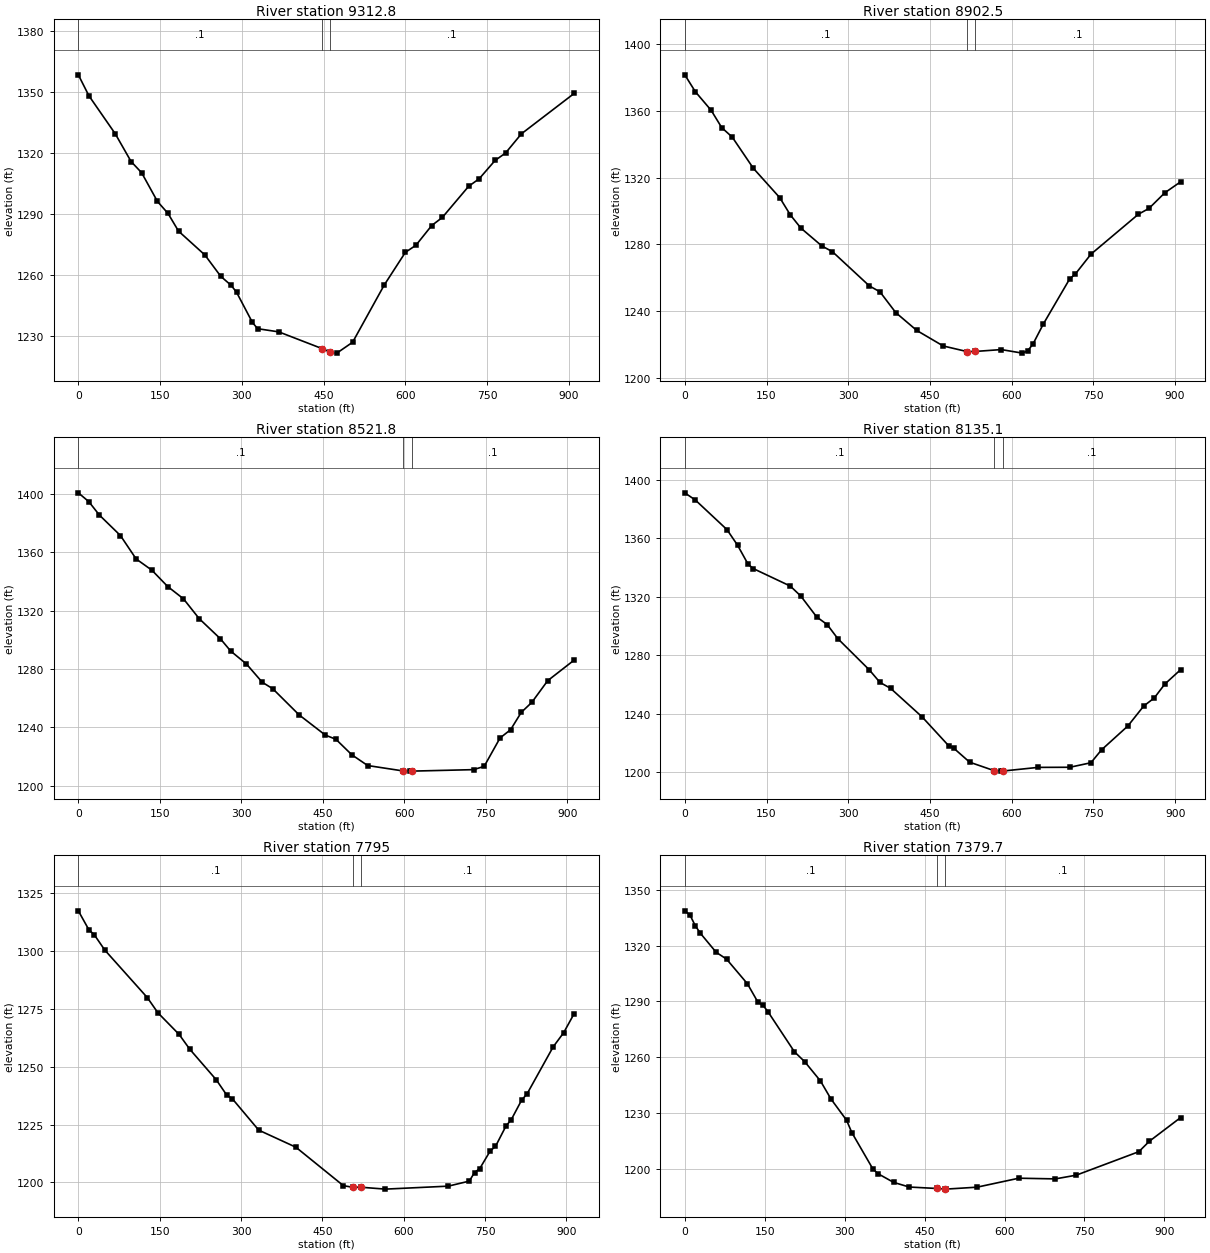
Type RM Length L Ch R = 1 ,9312.8  ,403.716,410.26,416.804
XS GIS Cut Line= 3
     1821696.439      341846.785     1822024.943      342161.602
     1822353.448      342476.419
#Sta/Elev= 30
       0 1358.38    19.4 1348.08    67.8 1329.35    96.8 1315.72   116.2 1310.18
   145.2 1296.07   164.6 1290.17   183.9 1281.46   232.3 1269.71   261.4 1259.22
   280.7 1254.72   290.4 1251.37   319.5 1236.52   329.1 1233.44   367.9 1231.88
   447.5 1223.63   462.5 1221.89   474.4 1221.42   503.4 1226.78   561.5 1254.97
   600.2 1271.01   619.6 1274.51   648.6 1284.22     668 1288.18   716.4 1303.53
   735.7 1307.23   764.8 1316.22   784.1 1319.91   813.2 1329.35     910 1349.22
#Mann= 3 , 0 , 0
       0      .1       0   447.5    .045       0   462.5      .1       0
Bank Sta=447.5,462.5
XS Rating Curve= 0 ,0
Exp/Cntr=0.3,0.1

Type RM Length L Ch R = 1 ,8902.5  ,385.594,380.735,375.876
XS GIS Cut Line= 3
     1821488.226       342003.51     1821709.896       342400.84
     1821939.181      342793.963
#Sta/Elev= 30
       0 1381.59    19.4 1371.45    48.4  1360.3    67.8 1349.93    87.1 1344.24
   125.8 1325.56   174.2 1307.98   193.6 1297.66     213 1289.72   251.7 1278.95
   271.1 1275.52   338.8 1255.02   358.2 1251.49   387.2 1239.04   425.9  1228.3
   474.3 1219.02   518.2 1215.65   533.2 1215.74   580.9 1216.86   619.6 1214.73
   629.3  1216.1     639 1220.13   658.3  1232.3   706.7 1259.36   716.4 1261.98
   745.5 1274.05   832.6 1298.01     852 1301.49     881 1310.84   910.1 1317.46
#Mann= 3 , 0 , 0
       0      .1       0   518.2    .045       0   533.2      .1       0
Bank Sta=518.2,533.2
XS Rating Curve= 0 ,0
Exp/Cntr=0.3,0.1

Type RM Length L Ch R = 1 ,8521.8  ,389.529,386.694,383.86
XS GIS Cut Line= 3
     1821039.213      342310.148     1821376.117      342615.183
     1821682.134      342955.882
#Sta/Elev= 30
       0 1400.94    19.3 1394.88    38.7 1385.69    77.4 1371.64   106.4 1355.54
   135.4 1347.81   164.4 1336.63   193.4  1328.2   222.4 1314.57   261.1 1300.87
   280.4  1292.3   309.4 1283.41   338.4  1270.9   357.8 1266.44   406.1 1248.55
   454.5 1234.62     474 1231.74   503.2 1221.12   532.4 1213.72   598.1 1209.98
   610.4 1209.88   613.1 1209.88   727.3  1210.9   746.8 1213.15     776 1232.63
   795.5 1238.35     815 1250.19   834.5 1257.08   863.7 1271.97   912.4 1286.11
#Mann= 3 , 0 , 0
       0      .1       0   598.1    .045       0   613.1      .1       0
Bank Sta=598.1,613.1
XS Rating Curve= 0 ,0
Exp/Cntr=0.3,0.1

Type RM Length L Ch R = 1 ,8135.1  ,355.397,340.058,324.719
XS GIS Cut Line= 3
     1820767.978      342618.296     1821112.257       342915.78
     1821456.917      343212.823
#Sta/Elev= 30
       0 1391.03    19.4 1386.09    77.4 1365.89    96.8 1355.26   116.2 1342.21
   125.9 1339.22   193.6 1327.32     213 1320.47     242 1306.24   261.4 1300.99
   280.7 1291.44   338.8 1269.99   358.2 1261.48   377.6 1257.47   435.6 1237.91
     484 1218.33   493.7 1216.51   522.8 1206.98   568.2 1201.14   580.9 1200.87
   583.2 1200.91   648.6 1203.43   706.7 1203.51   745.4  1206.6   764.8  1215.4
   813.2 1231.73   842.2 1245.33   861.6 1250.86     881 1260.35     910 1270.19
#Mann= 3 , 0 , 0
       0      .1       0   568.2    .045       0   583.2      .1       0
Bank Sta=568.2,583.2
XS Rating Curve= 0 ,0
Exp/Cntr=0.3,0.1

Type RM Length L Ch R = 1 ,7795    ,402.822,415.301,420.266
XS GIS Cut Line= 3
     1820507.926      343174.792     1820958.159      343267.822
     1821409.917       343318.35
#Sta/Elev= 30
       0 1317.48    19.6 1309.21    29.3 1307.16    48.9 1300.47   127.2 1279.93
   146.7 1273.36   185.9 1263.97   205.4 1257.61   254.3 1244.36   273.9 1237.65
   283.7 1236.22   332.6 1222.57   401.1 1215.18   488.8 1198.52   505.8 1197.85
   520.8 1197.86   566.1 1197.03   682.2 1198.32   720.9  1200.5   730.6 1204.22
   740.2 1205.92   759.6 1213.58   769.2  1215.5   788.6 1224.35   798.3 1227.09
   817.6 1235.62   827.3  1238.2   875.6 1258.61     895 1264.75   914.3    1273
#Mann= 3 , 0 , 0
       0      .1       0   505.8    .045       0   520.8      .1       0
Bank Sta=505.8,520.8
XS Rating Curve= 0 ,0
Exp/Cntr=0.3,0.1

Type RM Length L Ch R = 1 ,7379.7  ,386.169,388.673,398.691
XS GIS Cut Line= 3
     1820414.383      343371.658     1820816.417      343633.639
     1821252.438      343747.383
#Sta/Elev= 30
       0 1338.73     9.8 1336.41    19.6 1330.75    29.4 1326.59    58.8 1316.43
    78.3 1312.75   117.5 1299.47   137.1 1289.62   146.9 1287.87   156.7 1284.15
   205.7 1262.87   225.2 1257.46   254.6 1247.14   274.2 1237.49   303.6    1226
   313.4 1219.38   352.5    1200   362.3 1197.26   391.7 1192.57   421.1 1190.04
   472.4 1189.27   487.4 1188.93   489.7 1188.91   548.4 1189.96   626.8 1194.79
   695.4 1194.42   734.6 1196.42   852.1 1209.07   871.7 1214.65   930.5 1227.44
#Mann= 3 , 0 , 0
       0      .1       0   472.4    .045       0   487.4      .1       0
Bank Sta=472.4,487.4
XS Rating Curve= 0 ,0
Exp/Cntr=0.3,0.1

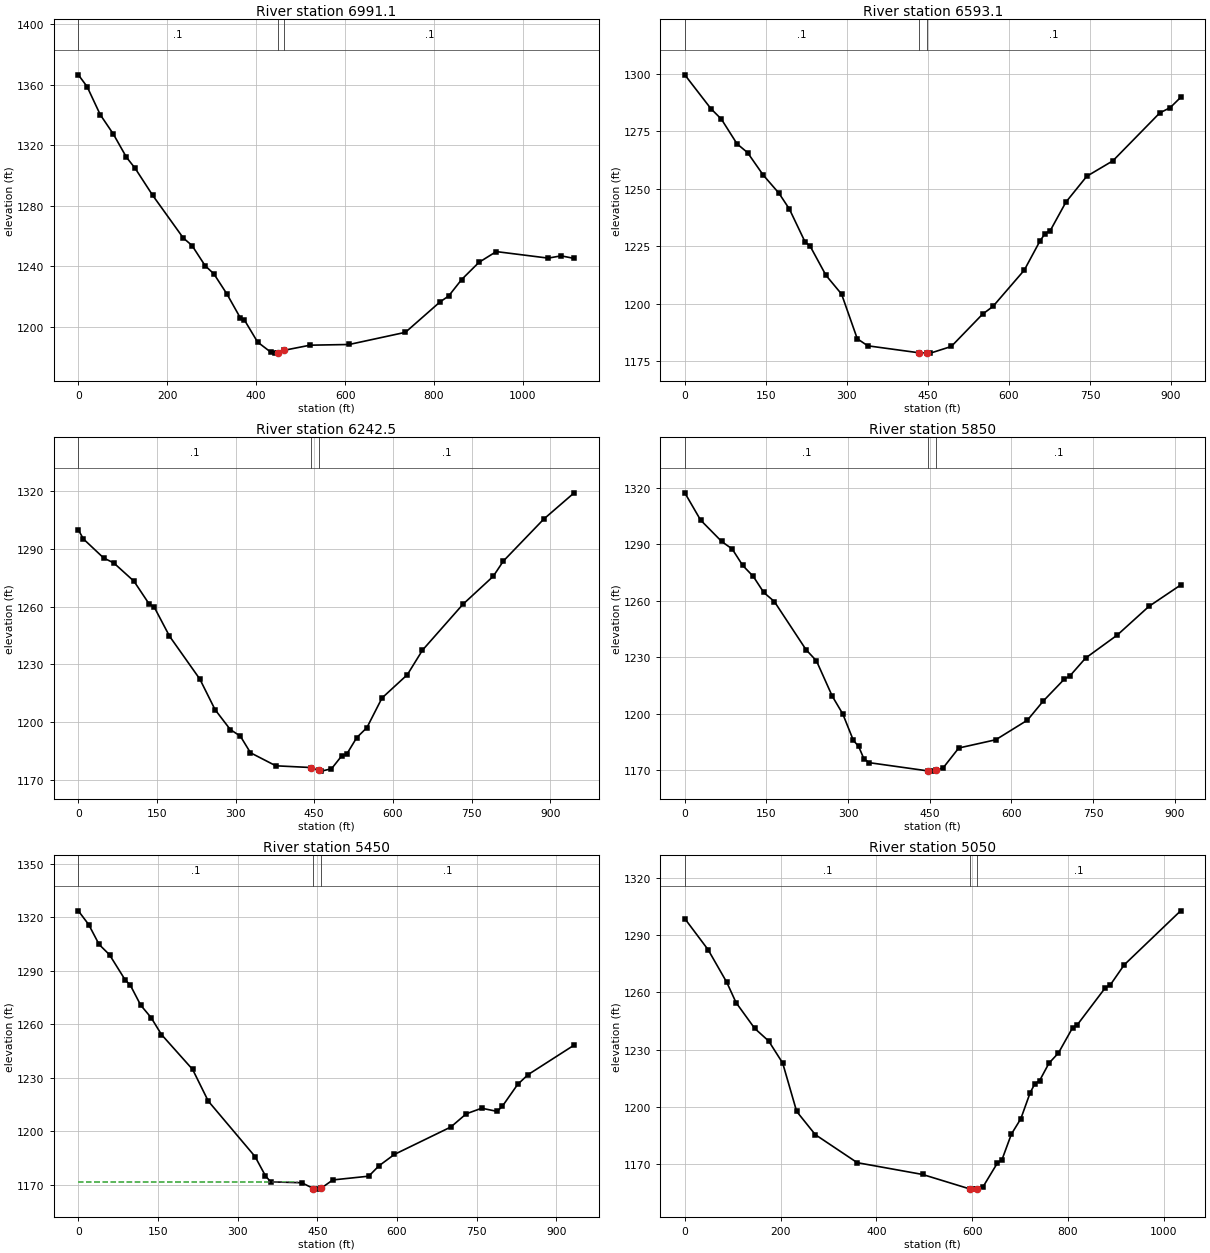
Type RM Length L Ch R = 1 ,6991.1  ,396.425,398.013,399.6
XS GIS Cut Line= 3
     1820189.761      343609.681     1820614.392      343960.381
      1820899.13      344447.815
#Sta/Elev= 30
       0 1366.42    19.7 1358.62    49.2 1340.11    78.7 1327.27   108.2 1311.91
   127.8  1304.6   167.2 1286.75     236 1258.55   255.7 1253.56   285.2  1240.2
   304.9  1234.8   334.4  1221.4   363.9 1205.94   373.7 1204.24   403.2 1189.71
   432.7 1183.08   442.5  1182.4   448.7 1182.78   463.7 1184.32   521.2 1187.65
   609.1 1188.11   735.7 1196.16   813.5 1216.25     833  1220.2   862.2 1231.08
   901.1 1242.43     940 1249.54  1056.8 1245.22    1086 1246.73  1115.2 1245.02
#Mann= 3 , 0 , 0
       0      .1       0   448.7    .045       0   463.7      .1       0
Bank Sta=448.7,463.7
XS Rating Curve= 0 ,0
Exp/Cntr=0.3,0.1

Type RM Length L Ch R = 1 ,6593.1  ,338.243,350.547,362.877
XS GIS Cut Line= 3
     1820005.744      343923.444     1820341.295      344244.334
     1820653.125       344573.43
#Sta/Elev= 30
       0 1299.54    48.4  1284.8    67.7 1280.27    96.7 1269.51   116.1 1265.73
   145.1 1255.96   174.1  1248.1   193.5  1241.2   222.5 1226.91   232.1 1224.98
   261.2 1212.38   290.2 1204.16   319.2 1184.78   338.5  1181.7   433.4 1178.66
   448.4 1178.53   454.6 1178.51   493.2  1181.4   551.1 1195.45   570.4 1198.82
   628.3 1214.59   657.2  1227.2   666.9 1230.53   676.5 1231.82   705.4 1244.18
     744 1255.42   792.3 1262.14   879.1 1282.97   898.4 1285.27   917.7 1289.72
#Mann= 3 , 0 , 0
       0      .1       0   433.4    .045       0   448.4      .1       0
Bank Sta=433.4,448.4
XS Rating Curve= 0 ,0
Exp/Cntr=0.3,0.1

Type RM Length L Ch R = 1 ,6242.5  ,386.668,392.47,398.648
XS GIS Cut Line= 3
     1819916.584      343983.157     1820040.256         344440.
      1820026.88      344912.274
#Sta/Elev= 30
       0  1299.9     9.7 1295.17    48.3 1285.29    67.6 1282.72   106.2  1273.2
   135.2 1261.34   144.9 1259.72   173.9 1244.69   231.8 1222.38   260.8 1206.52
   289.8  1196.2   309.1 1192.74   328.4 1184.12   376.7 1177.35   443.3 1176.45
   458.3 1174.92   463.6 1174.58   482.9  1175.8   502.2 1182.42   511.9 1183.37
   531.1    1192   550.4 1197.15   579.3 1212.58   627.6 1224.68   656.5 1237.42
   733.6 1261.23   791.5 1275.79   810.8 1283.71   887.9 1305.51   945.8 1319.14
#Mann= 3 , 0 , 0
       0      .1       0   443.3    .045       0   458.3      .1       0
Bank Sta=443.3,458.3
XS Rating Curve= 0 ,0
Exp/Cntr=0.3,0.1

Type RM Length L Ch R = 1 ,5850    ,400.477,400,391.511
XS GIS Cut Line= 3
     1819660.536      344043.404     1819661.008      344498.205
     1819653.334      344954.271
#Sta/Elev= 30
       0 1317.24      29 1302.79    67.7 1291.44    87.1 1287.44   106.4 1278.72
   125.8  1272.9   145.1 1264.37   164.5 1259.58   222.6 1234.08   241.9 1228.08
   270.9 1209.38   290.3  1199.9   309.7 1185.91   319.3 1182.77     329 1176.16
   338.7  1174.1   447.3  1169.7   454.8 1169.61   462.3 1170.41   474.2 1171.18
   503.3 1181.87   571.3 1186.25   629.5 1196.66   658.6 1206.81   697.4 1218.46
   707.1 1219.99   736.2 1229.55   794.5 1241.79   852.7 1257.01   910.9 1268.32
#Mann= 3 , 0 , 0
       0      .1       0   447.3    .045       0   462.3      .1       0
Bank Sta=447.3,462.3
XS Rating Curve= 0 ,0
Exp/Cntr=0.3,0.1

Type RM Length L Ch R = 1 ,5450    ,389.531,400,407.486
XS GIS Cut Line= 3
     1819252.994      344071.953     1819262.991      344521.835
     1819427.995       344976.17
#Sta/Elev= 30
       0 1323.72    19.6 1315.95    39.1 1304.83    58.7 1299.05      88    1285
    97.8    1282   117.4 1270.74     137 1263.74   156.5 1254.24   215.2 1234.62
   244.6 1216.86   332.6 1185.74   352.2 1174.92     362 1171.51   420.6 1171.01
   442.5 1167.76     450 1167.42   457.5    1168     479 1172.58   546.7 1174.69
     566 1180.53     595 1186.91   701.3 1202.32   730.3 1209.73   759.4 1212.86
   788.4 1211.07     798 1213.86     827 1226.22   846.4 1231.67   933.4 1248.31
#Mann= 3 , 0 , 0
       0      .1       0   442.5    .045       0   457.5      .1       0
#XS Ineff= 2 , 0
          410.94 1171.39
Permanent Ineff=
       F       F
Bank Sta=442.5,457.5
XS Rating Curve= 0 ,0
Exp/Cntr=0.3,0.1

Type RM Length L Ch R = 1 ,5050    ,269.72,274.751,290.289
XS GIS Cut Line= 3
      1819103.33         344089.     1818924.205      344665.048
     1818956.568      345095.531
#Sta/Elev= 30
       0 1298.65    48.6  1282.4    87.6 1265.33     107  1254.7   145.9  1241.2
   175.1 1234.59   204.3 1223.07   233.5 1197.75   272.4 1185.61     360 1170.93
   496.2 1164.77   595.8 1157.12   603.3 1157.09   610.8 1157.23   622.9 1158.45
   652.3 1170.66   662.1  1172.5   681.7 1185.86   701.4 1193.91     721  1207.6
   730.8 1212.23   740.6 1213.85   760.2    1223   779.9 1228.32   809.3 1241.46
   819.1 1243.01     878 1262.53   887.8 1263.81   917.2 1274.45    1035 1302.73
#Mann= 3 , 0 , 0
       0      .1       0   595.8    .045       0   610.8      .1       0
Bank Sta=595.8,610.8
XS Rating Curve= 0 ,0
Exp/Cntr=0.3,0.1

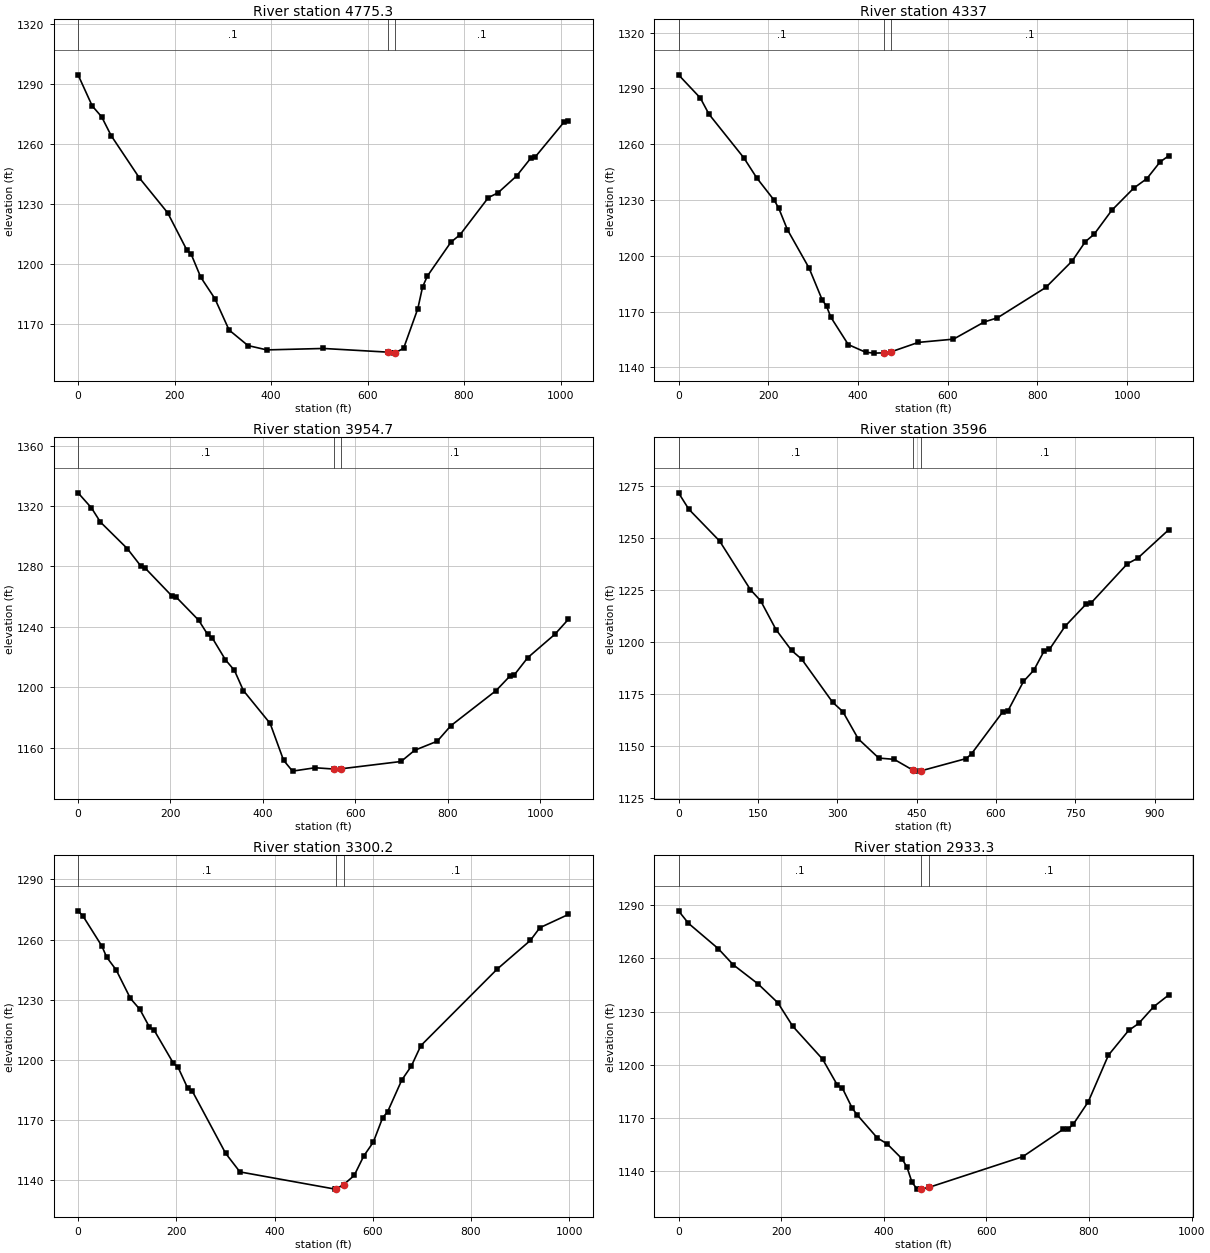
Type RM Length L Ch R = 1 ,4775.3  ,432.577,438.305,442.824
XS GIS Cut Line= 3
     1819014.071      344054.513      1818611.57      344679.466
     1818650.178      344949.727
#Sta/Elev= 30
       0 1294.42    29.3  1278.9    48.9 1273.46    68.5  1264.1   127.2  1242.9
   185.8  1225.5     225 1207.15   234.7 1204.71   254.3 1193.35   283.6 1182.66
     313    1167   352.1 1159.24   391.2 1157.06   508.6 1157.78   642.5 1155.94
   655.3 1155.45   657.5 1155.58   674.9 1157.94   704.2 1177.63     714  1188.4
   723.8 1193.85   772.6 1210.78   792.1 1214.67   850.6 1233.16   870.1 1235.44
   909.1 1243.95   938.4 1252.83   948.1 1253.56  1006.6 1270.62  1016.4 1271.29
#Mann= 3 , 0 , 0
       0      .1       0   642.5    .045       0   657.5      .1       0
Bank Sta=642.5,657.5
XS Rating Curve= 0 ,0
Exp/Cntr=0.3,0.1

Type RM Length L Ch R = 1 ,4337    ,393.517,382.286,372.086
XS GIS Cut Line= 3
     1818965.771      343993.313     1818578.101      344214.556
     1818137.522      344687.816
#Sta/Elev= 30
       0 1297.28    48.5 1284.87    67.9 1276.12   145.6 1252.66   174.7 1241.76
   213.5 1229.76   223.2 1225.69   242.6  1214.1   291.1 1193.36   320.2 1176.34
   329.9  1172.9   339.6 1166.95   378.4 1152.26   417.2 1148.13   436.7 1147.67
   458.1 1147.84   473.1 1148.31   534.5 1153.44   612.9 1155.18   681.5 1164.43
   710.9 1166.65   818.6 1182.96   877.4 1197.19   906.8  1207.6   926.4 1211.58
   965.6 1224.42  1014.6 1236.35    1044  1241.5  1073.4 1250.46    1093 1253.81
#Mann= 3 , 0 , 0
       0      .1       0   458.1    .045       0   473.1      .1       0
Bank Sta=458.1,473.1
XS Rating Curve= 0 ,0
Exp/Cntr=0.3,0.1

Type RM Length L Ch R = 1 ,3954.7  ,366.986,358.668,350.35
XS GIS Cut Line= 3
     1818168.303      343606.845     1818227.666        344067.2
      1818057.23      344639.607
#Sta/Elev= 30
       0 1328.82      29 1318.82    48.4 1309.44   106.4 1291.91   135.4 1280.49
   145.1 1278.97   203.1 1260.46   212.7 1259.61   261.1 1244.38   280.4 1234.97
   290.1 1232.86   319.1 1218.12   338.5 1211.13   357.8 1197.79   415.8 1175.96
   444.8 1151.58   464.2 1144.37   513.1 1146.61   554.7 1145.72   569.7 1145.93
   699.1 1150.76   728.5 1158.17   777.5 1164.21   806.8 1174.44   904.8 1197.74
   934.1 1207.16   943.9 1208.03   973.3 1219.56    1032 1235.04  1061.4 1245.03
#Mann= 3 , 0 , 0
       0      .1       0   554.7    .045       0   569.7      .1       0
Bank Sta=554.7,569.7
XS Rating Curve= 0 ,0
Exp/Cntr=0.3,0.1

Type RM Length L Ch R = 1 ,3596    ,291.641,295.833,296.18
XS GIS Cut Line= 3
     1817835.885      343748.371     1817854.798      344242.826
     1817898.029      344672.434
#Sta/Elev= 30
       0 1271.72    19.4 1263.85    77.6 1248.55   135.8 1225.16   155.2 1219.79
   184.3 1205.89   213.5 1195.94   232.9 1191.66   291.1 1171.02   310.5 1166.47
   339.6 1153.39   378.4 1144.13   407.5 1143.52   442.5 1138.38   446.3 1137.85
   457.5 1137.94   543.9 1143.91   553.7  1146.2   612.6 1166.33   622.4 1166.82
   651.8 1180.97   671.5 1186.43   691.1 1195.76   700.9 1196.42   730.3 1207.49
   769.6 1218.04   779.4 1218.69   848.1 1237.59   867.7 1240.27   926.6 1254.03
#Mann= 3 , 0 , 0
       0      .1       0   442.5    .045       0   457.5      .1       0
Bank Sta=442.5,457.5
XS Rating Curve= 0 ,0
Exp/Cntr=0.3,0.1

Type RM Length L Ch R = 1 ,3300.2  ,361.228,366.94,373.14
XS GIS Cut Line= 3
     1817690.228      343746.329     1817594.164      344270.804
     1817564.779       344735.17
#Sta/Elev= 30
       0 1274.34     9.7 1271.85    48.5 1256.75    58.2 1251.24    77.6 1244.86
   106.6 1230.66     126 1225.12   145.4 1216.32   155.1 1214.71   193.9 1198.38
   203.6  1196.3     223 1185.98   232.7 1184.36   300.5 1153.36   329.6 1144.09
   523.5  1135.5   525.7 1135.61   540.7 1137.74   562.3 1142.32   581.7 1152.02
   601.1 1158.89   620.4 1171.23   630.1 1173.98   659.2 1189.94   678.6 1196.88
     698 1207.08   853.1 1245.19   920.9 1259.55   940.3 1265.91   998.5 1272.54
#Mann= 3 , 0 , 0
       0      .1       0   525.7    .045       0   540.7      .1       0
Bank Sta=525.7,540.7
XS Rating Curve= 0 ,0
Exp/Cntr=0.3,0.1

Type RM Length L Ch R = 1 ,2933.3  ,381.188,380.53,384.318
XS GIS Cut Line= 3
     1817465.892       343640.17     1817334.954      344065.717
     1817082.789      344509.394
#Sta/Elev= 30
       0 1286.75    19.4 1279.71    77.4 1265.46   106.5 1256.41   154.9 1245.61
   193.6 1234.97   222.6 1221.76   280.7 1203.25   309.7 1188.52   319.4 1186.86
   338.8 1175.45   348.4 1171.77   387.2  1158.9   406.5 1155.51   435.6 1147.09
   445.2 1142.38     455  1133.9   464.9 1130.02   472.7 1130.12   487.7 1130.98
     671 1148.32   749.5 1163.68   759.3 1163.83   769.1  1166.5   798.5 1179.21
   837.8 1205.47   877.1 1219.37   896.7 1223.31   926.1 1232.77   955.6 1239.43
#Mann= 3 , 0 , 0
       0      .1       0   472.7    .045       0   487.7      .1       0
Bank Sta=472.7,487.7
XS Rating Curve= 0 ,0
Exp/Cntr=0.3,0.1

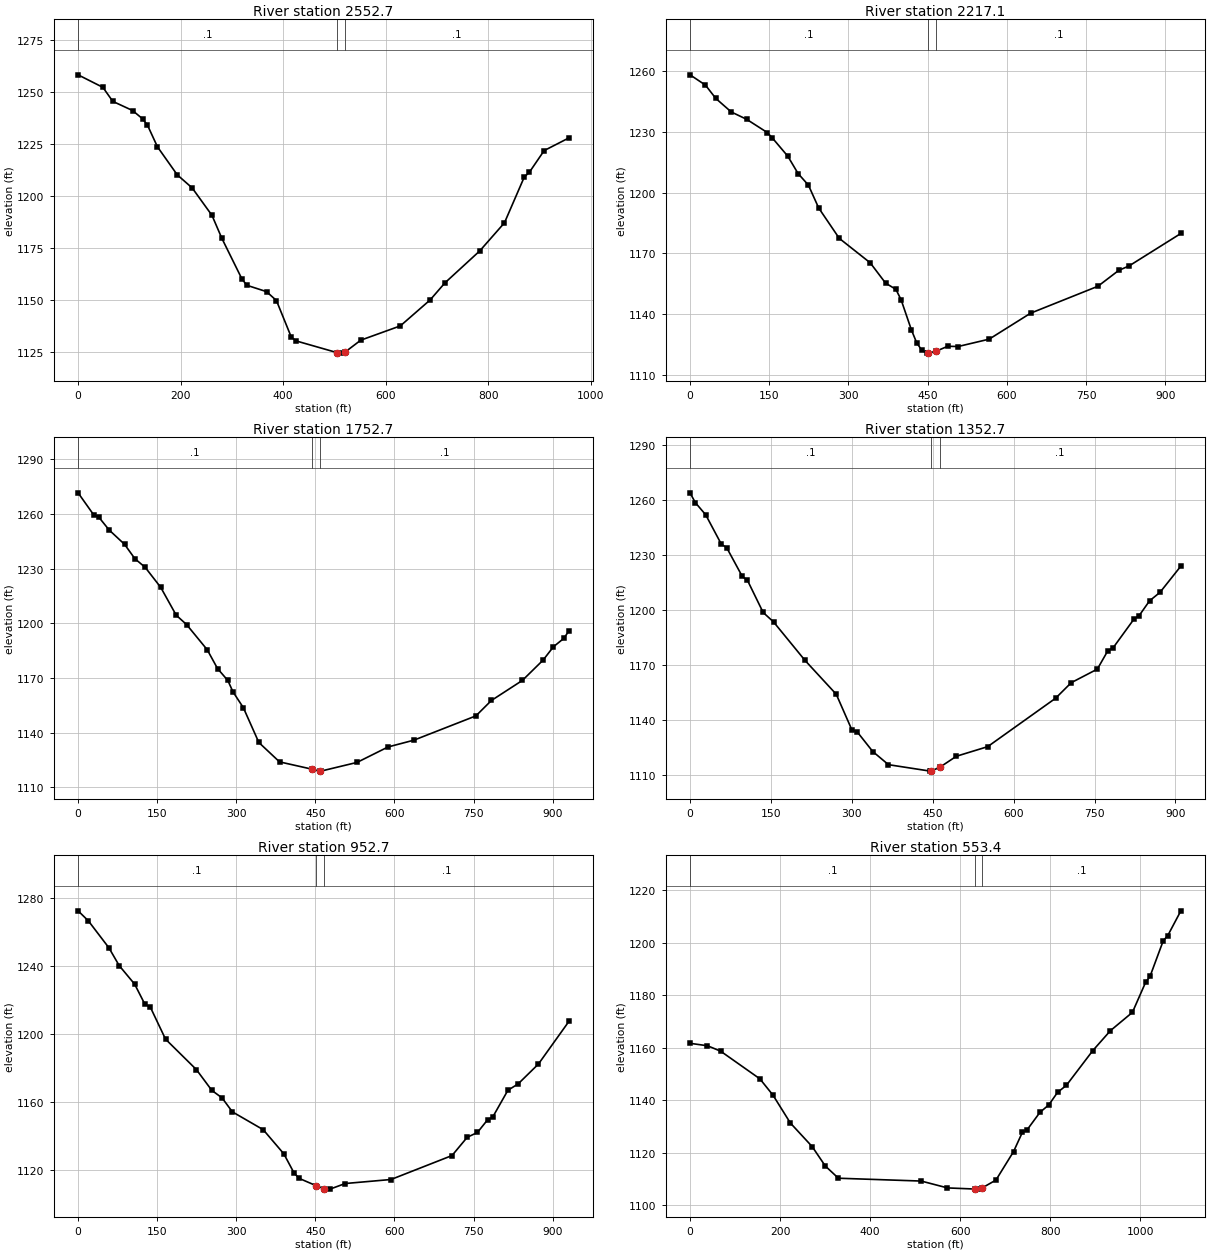
Type RM Length L Ch R = 1 ,2552.7  ,329.862,335.595,336.881
XS GIS Cut Line= 3
     1817190.733       343561.23     1816950.694      344014.274
     1816670.196      344359.502
#Sta/Elev= 30
       0  1258.3    48.4 1252.27    67.7 1245.52   106.4  1241.1   125.8 1237.11
   135.4 1234.05   154.8 1223.64   193.5 1210.13   222.5 1203.86   261.2 1190.63
   280.5 1179.55   319.2 1160.21   328.9 1156.99   367.6  1153.9   386.9 1149.63
     416 1131.95   425.6 1130.15   505.2 1124.53   512.7 1124.29   520.2 1124.67
   551.4 1130.52   628.7 1137.41   686.8 1149.91   715.8 1158.16   783.5 1173.49
   831.8 1187.06   870.5 1209.13   880.2 1211.32   909.2 1221.82   957.5 1227.92
#Mann= 3 , 0 , 0
       0      .1       0   505.2    .045       0   520.2      .1       0
Bank Sta=505.2,520.2
XS Rating Curve= 0 ,0
Exp/Cntr=0.3,0.1

Type RM Length L Ch R = 1 ,2217.1  ,484.288,464.406,451.077
XS GIS Cut Line= 3
     1817086.529      343453.643     1816796.964      343699.773
     1816425.084      344104.115
#Sta/Elev= 30
       0 1258.25    29.2 1253.16    48.7  1246.6      78 1239.89   107.2 1236.25
   146.2 1229.72   155.9 1227.01   185.1 1218.01   204.6 1209.42   224.1 1203.71
   243.6  1192.4   282.6 1177.37   341.1  1165.3   370.3 1155.23   389.8 1152.17
   399.7 1146.96   419.3 1131.99   429.1 1125.78   438.9    1122   448.7 1120.62
   450.3 1120.66   465.3 1121.49   487.9 1124.01   507.6 1123.89   566.4 1127.53
   644.9 1140.38   772.4  1153.7   811.7 1161.53   831.3 1163.74   929.4  1179.8
#Mann= 3 , 0 , 0
       0      .1       0   450.3    .045       0   465.3      .1       0
Bank Sta=450.3,465.3
XS Rating Curve= 0 ,0
Exp/Cntr=0.3,0.1

Type RM Length L Ch R = 1 ,1752.7  ,393.363,400,398.995
XS GIS Cut Line= 3
     1816352.884      343088.274     1816381.726       343537.91
     1816258.121      344001.921
#Sta/Elev= 30
       0 1271.57    29.4 1259.57    39.2 1258.26    58.8 1251.21    88.2 1243.29
   107.7 1235.44   127.3 1230.67   156.7 1219.72   186.1 1204.43   205.7 1199.32
   244.9 1185.49   264.5 1175.15     284 1168.62   293.8 1162.37   313.4 1153.71
   342.8 1134.61     382 1123.98   443.1    1120   458.1 1118.92   460.4  1118.9
     529 1123.68   587.8 1132.16   636.8 1135.88   754.4  1149.2   783.8 1157.65
   842.6 1168.67   881.8 1179.79   901.4  1187.1     921  1191.7   930.8 1195.78
#Mann= 3 , 0 , 0
       0      .1       0   443.1    .045       0   458.1      .1       0
Bank Sta=443.1,458.1
XS Rating Curve= 0 ,0
Exp/Cntr=0.3,0.1

Type RM Length L Ch R = 1 ,1352.7  ,397.132,400,396.675
XS GIS Cut Line= 3
     1816089.129      343064.779     1815985.577      343507.841
     1815883.267      343951.188
#Sta/Elev= 30
       0 1263.88     9.7 1258.58      29 1251.93    58.1 1235.87    67.8 1234.09
    96.8 1218.39   106.5  1216.2   135.5 1198.75   154.9 1193.56     213 1172.68
   271.1 1154.19   300.1 1134.77   309.8 1133.76   338.8 1123.01   367.9 1115.86
   445.3 1112.35   447.5 1112.53   462.5 1114.34   493.7 1120.44   551.8 1125.67
   677.7 1152.03   706.7  1160.5   755.1 1167.89   774.5 1177.85   784.2 1179.43
   822.9 1195.07   832.6    1197   851.9 1205.06   871.3 1209.69     910 1223.98
#Mann= 3 , 0 , 0
       0      .1       0   447.5    .045       0   462.5      .1       0
Bank Sta=447.5,462.5
XS Rating Curve= 0 ,0
Exp/Cntr=0.3,0.1

Type RM Length L Ch R = 1 ,952.7   ,407.802,399.329,397.113
XS GIS Cut Line= 3
     1815769.369       342962.09     1815611.849      343392.623
     1815562.414      343862.402
#Sta/Elev= 30
       0 1272.17    19.5 1266.27    58.5 1250.41      78 1239.94   107.3 1229.04
   126.8 1217.17   136.6 1215.82   165.8 1196.74   224.3 1178.84   253.6 1166.62
   273.1 1162.17   292.6 1153.98   351.1 1143.49   390.2 1129.29   409.7 1117.96
   419.4 1114.85   450.9 1110.65   465.9 1108.84   477.7 1108.55   506.6 1111.85
   593.4 1114.21   709.1 1128.29     738 1139.04   757.3 1141.85   776.6 1149.33
   786.2 1150.86   815.1 1166.67   834.4 1170.39     873  1182.1   930.8 1207.16
#Mann= 3 , 0 , 0
       0      .1       0   450.9    .045       0   465.9      .1       0
Bank Sta=450.9,465.9
XS Rating Curve= 0 ,0
Exp/Cntr=0.3,0.1

Type RM Length L Ch R = 1 ,553.4   ,421.576,406.291,389.088
XS GIS Cut Line= 3
     1815373.271      342831.079     1815238.141      343376.425
      1815241.96       343904.35
#Sta/Elev= 30
       0 1161.71    38.7 1160.78    67.8 1158.73     155  1148.2   184.1    1142
   222.8 1131.37   271.2  1122.4   300.3 1115.02   329.4 1110.37   513.4 1109.29
   571.6 1106.68   632.9 1106.25   640.1 1106.22   647.9 1106.62   679.2 1109.67
   718.3 1120.51   737.8 1127.82   747.6 1128.61   776.9 1135.44   796.5 1138.27
     816 1143.04   835.6 1145.72   894.2 1158.93   933.4 1166.53   982.2 1173.49
  1011.6 1184.96  1021.3 1187.18  1050.7 1200.76  1060.4 1202.62  1089.8 1212.13
#Mann= 3 , 0 , 0
       0      .1       0   632.9    .045       0   647.9      .1       0
Bank Sta=632.9,647.9
XS Rating Curve= 0 ,0
Exp/Cntr=0.3,0.1

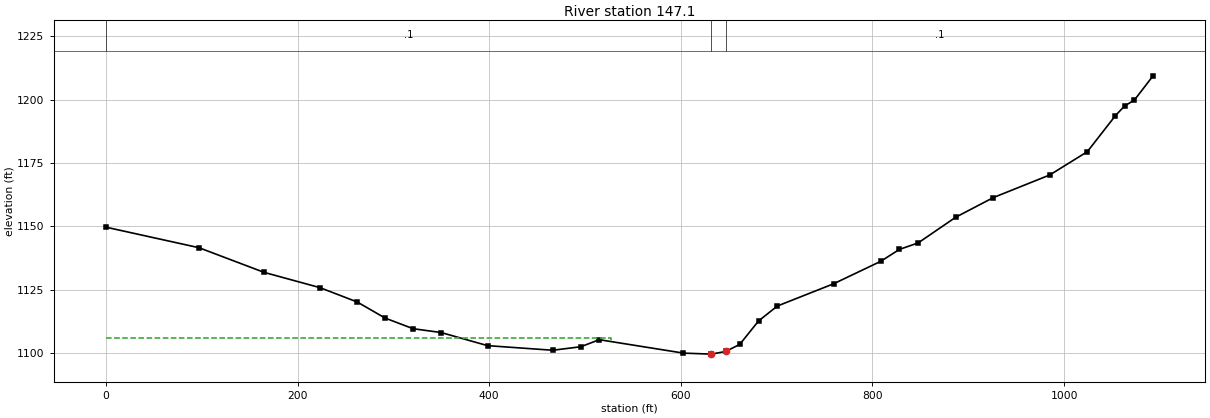
Type RM Length L Ch R = 1 ,147.1   ,149.581,147.102,144.656
XS GIS Cut Line= 3
     1814847.229      342917.948     1814871.858      343480.879
     1815144.309      343934.728
#Sta/Elev= 30
       0 1149.64    97.1 1141.53   165.2 1131.77   223.4 1125.75   262.3 1120.08
   291.4 1113.73   320.6 1109.53   349.7 1108.03   398.3 1102.84   466.3 1101.02
   495.5  1102.4   514.9 1105.19   602.7 1099.89   631.8 1099.49   646.8 1100.54
   661.5 1103.34   681.1 1112.59   700.7 1118.49   759.5 1127.29   808.5 1136.13
   828.1 1140.85   847.7 1143.43     887  1153.6   926.2 1161.34     985 1170.26
  1024.2 1179.45  1053.6 1193.73  1063.4 1197.62  1073.2 1199.78  1092.8 1209.42
#Mann= 3 , 0 , 0
       0      .1       0   631.8    .045       0   646.8      .1       0
#XS Ineff= 2 , 0
          527.19 1105.76
Permanent Ineff=
       F       F
Bank Sta=631.8,646.8
XS Rating Curve= 0 ,0
Exp/Cntr=0.3,0.1

Chan Stop Cuts=-1
Use User Specified Reach Order=0